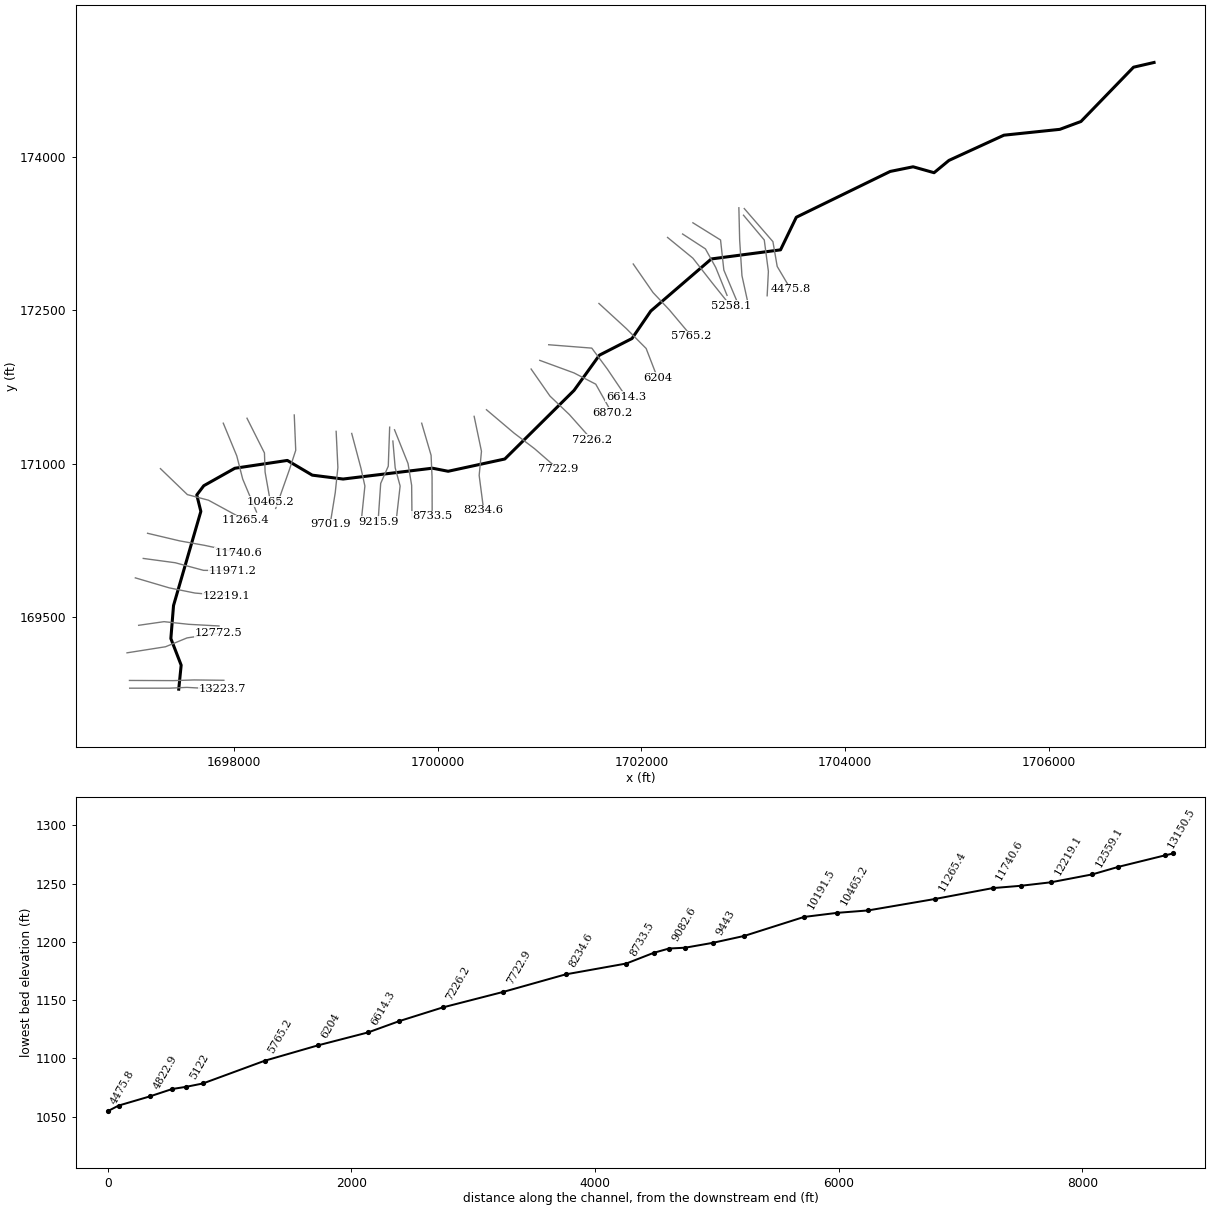
--- Greenbrier Fork.prj (project) ---

Proj Title=Greenbrier Fork
Current Plan=p01
Default Exp/Contr=0,0
English Units
Geom File=g01
Flow File=f01
Plan File=p01
BEGIN DESCRIPTION:
END DESCRIPTION:
DSS Export Rating Curves= 0
DSS Export Rating Curve Sorted= 0
DSS Export Volume Flow Curves= 0
DXF OffsetX= 0
DXF OffsetY= 0
DXF ScaleX= 0
DXF ScaleY= 0

--- Greenbrier Fork.p01 (plan) ---

Plan Title=Floodplain
Program Version=4.00
Geom File=g01
Flow File=f01
K Sum by GR=0
Std Step Tol=0.01
Critical Tol=0.01
Num of Std Step Trials=20
Max Error Tol=0.3
Flow Tol Ratio=0.001
Split Flow NTrial=30
Split Flow Tol=0.02
Split Flow Ratio=0.02
Log Output Level=0
Friction Slope Method=1
Unsteady Friction Slope Method=2
Unsteady Bridges Friction Slope Method=1
Global Log Level=0
CheckData=False
Run HTab=0
Run UNet=0
Run PostProcess=0
UNET Theta=0
UNET Theta Warmup=0
UNET ZTol=0
UNET ZSATol=0
UNET MxIter=0
UNET MaxInSteps=0
UNET DtIC=0
UNET DtMin=0
UNET MaxCRTS=0
UNET WFStab=0
UNET SFStab=0
UNET WFX=0
UNET SFX=0
UNET DSS MLevel=0
UNET DZMax Abort=0
UNET Convert EG Bridges=0
UNET Use Existing IB Tables=0
UNET Froude Limit=0
UNET Froude Power=0
Write IC File=0
Echo Input=False
Echo Output=False
Write Detailed=0

--- Greenbrier Fork.f01 (steady flow) ---

Flow Title=NFF Regression Equation
Program Version=4.00
Number of Profiles=1
Profile Names=P100yr
River Rch & RM=Greenbrier Fork,Main      ,13223.7
525.0549
River Rch & RM=Greenbrier Fork,Main      ,13223.7
577.9099
River Rch & RM=Greenbrier Fork,Main      ,12559.1
628.5913
River Rch & RM=Greenbrier Fork,Main      ,10717.7
656.1679
River Rch & RM=Greenbrier Fork,Main      ,9443
723.3410
River Rch & RM=Greenbrier Fork,Main      ,6870.2
799.5771
River Rch & RM=Greenbrier Fork,Main      ,4475.8
879.9222
River Rch & RM=Greenbrier Fork,Main      ,4175.2
1024.941
River Rch & RM=Greenbrier Fork,Main      ,3302.1
1041.036
River Rch & RM=Greenbrier Fork,Main      ,286.1
1156.141
Boundary for River Rch & Prof#=Greenbrier Fork,Main      ,1
Up Type=0
Dn Type=3
Dn Slope=0.032645

--- Greenbrier Fork.g01 (geometry) ---

Geom Title=USGS 10m DEM
Program Version=4.00

River Reach=Greenbrier Fork ,Main
Reach XY= 30
     1697455.587      168793.166      1697479.42      169028.073
     1697378.184      169288.309     1697404.369      169611.029
     1697672.757      170532.059     1697632.826      170693.091
      1697701.56      170783.427     1698006.605      170954.279
     1698522.434      171030.867     1698767.256      170886.855
     1699070.338      170848.887     1699947.509      170954.933
     1700101.996      170924.821     1700658.641      171044.898
     1701338.837      171715.938     1701587.911      172060.632
     1701908.173      172223.698     1702092.661       172492.42
     1702687.117      173001.955     1703367.094      173091.064
     1703521.988      173409.822     1704444.327      173858.012
     1704669.308       173903.47     1704875.323      173845.591
     1705021.401      173965.863     1705561.563      174212.621
     1706110.554      174269.756     1706318.215      174346.594
     1706834.676      174877.745     1707036.368      174923.976

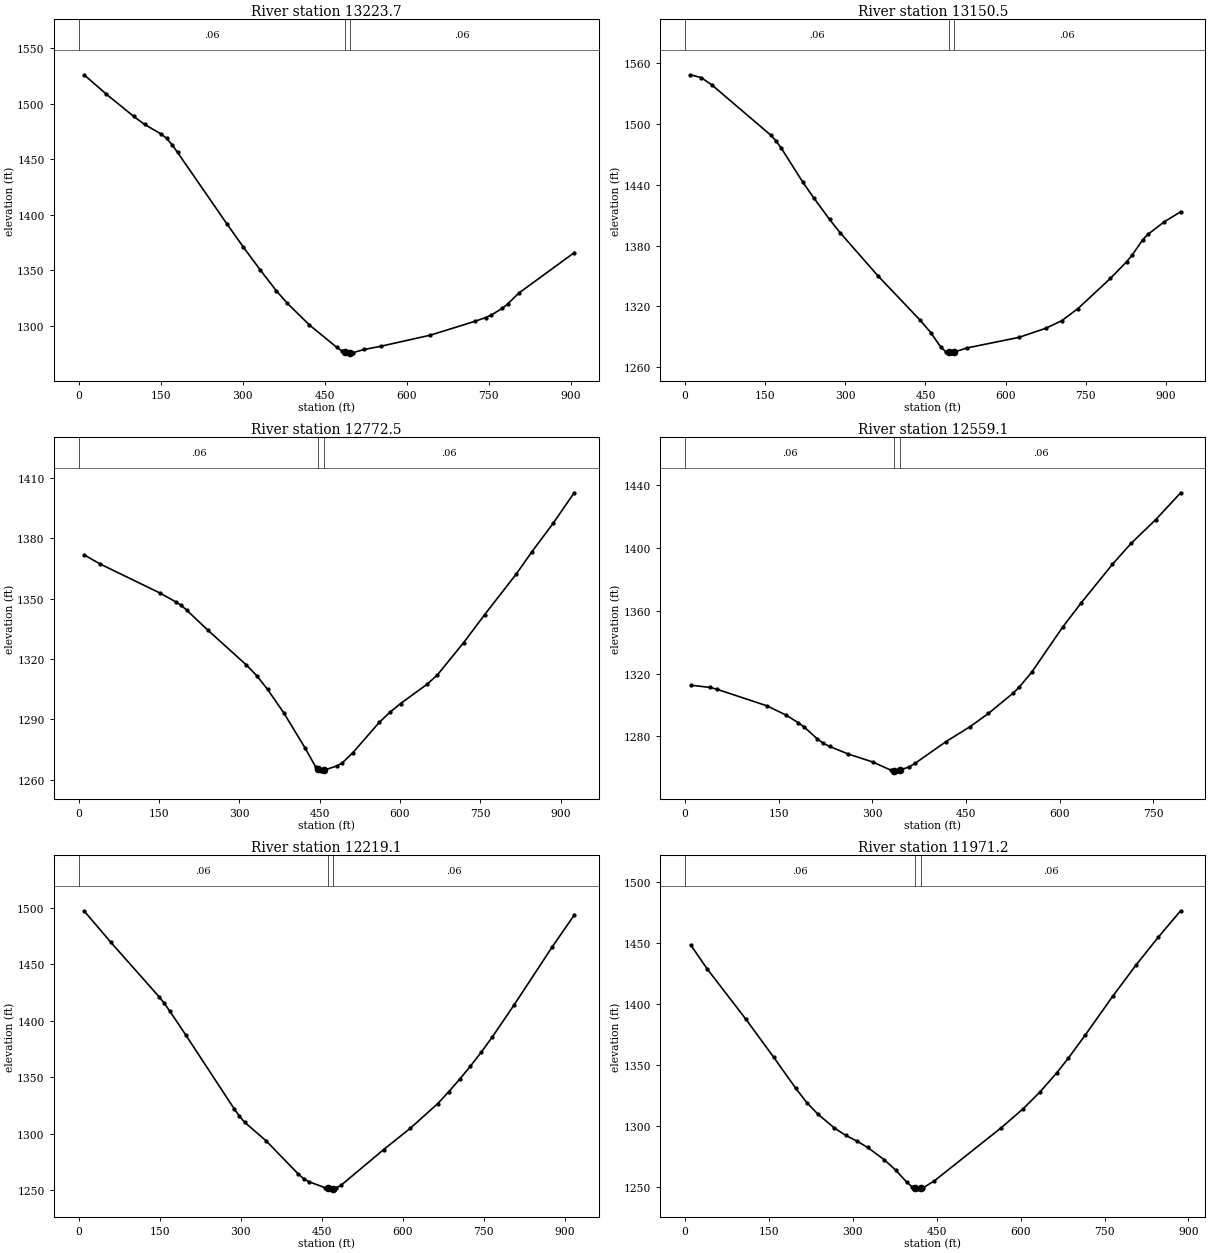
Type RM Length L Ch R = 1 ,13223.7 ,73.8,73.2,72.6
XS GIS Cut Line= 4
      1696973.66      168802.773     1697365.387      168802.843
     1697535.716      168810.585     1697878.953       168792.52
#Sta/Elev= 30
      10 1526.09    50.2 1508.84   100.4 1488.77   120.5 1481.43   150.7 1472.83
   160.7 1468.95   170.8 1463.22   180.8 1456.27   271.2 1391.82   301.3 1370.94
   331.5 1350.83   361.6 1331.63   381.7 1320.42   421.8 1301.01     472 1280.84
     482 1277.27     487 1276.59     492 1275.91     497 1276.04   502.1 1276.18
   522.1 1278.93   552.2 1281.82   643.1 1291.82     724  1304.2   744.2 1307.69
   754.3 1309.95   774.5 1315.93   784.6 1319.98   804.9 1329.72   905.9 1366.01
#Mann= 3 , 0 , 0
       0     .06       0     487    .045       0     497     .06       0
Bank Sta=487,497
XS Rating Curve= 0 ,0
Exp/Cntr=0.3,0.1

Type RM Length L Ch R = 1 ,13150.5 ,370.8,378,385.2
XS GIS Cut Line= 4
     1696971.491      168878.492     1697402.134      168876.835
      1697605.86      168883.461     1697899.028      168880.148
#Sta/Elev= 30
      10 1548.71      30 1545.92    50.1 1538.72   160.2 1489.19   170.3 1483.35
   180.3 1476.09   220.3 1442.75   240.4  1427.5   270.4  1405.9   290.4 1392.64
   360.5 1350.48   440.4 1306.17   459.8 1294.19   479.2 1279.42   488.9  1274.9
   493.6 1274.54   498.6 1274.14   503.6  1274.9   527.7 1278.96   624.8 1289.38
   674.9 1298.34   705.2 1305.88   735.6  1317.9   796.2 1347.63   826.6  1364.1
   836.7 1370.44   856.9 1385.95     867 1391.34   897.3 1403.62   927.7 1413.42
#Mann= 3 , 0 , 0
       0     .06       0   493.6    .045       0   503.6     .06       0
Bank Sta=493.6,503.6
XS Rating Curve= 0 ,0
Exp/Cntr=0.3,0.1

Type RM Length L Ch R = 1 ,12772.5 ,223.3,213.4,203.5
XS GIS Cut Line= 4
     1696947.541      169148.726     1697325.943      169208.099
     1697536.733      169294.586     1697847.661      169340.728
#Sta/Elev= 30
    10.1 1371.83    40.3 1367.24   151.2 1352.91   181.4 1348.42   191.5 1346.67
   201.6 1344.37   241.9  1334.2   312.5 1317.21   332.6 1311.72   352.8 1304.89
     383 1293.24   422.7  1275.8   442.5 1266.38   447.4 1265.39   452.4 1264.39
   457.4 1264.65   482.1 1266.82     492 1268.28   511.8 1273.36   561.3 1288.49
   581.2 1293.51     601 1297.85   650.2 1307.37   669.8 1312.08   718.9 1328.17
   758.2 1342.12   817.2 1362.33   846.6 1373.46   885.9 1387.47   925.2 1402.68
#Mann= 3 , 0 , 0
       0     .06       0   447.4    .045       0   457.4     .06       0
Bank Sta=447.4,457.4
XS Rating Curve= 0 ,0
Exp/Cntr=0.3,0.1

Type RM Length L Ch R = 1 ,12559.1 ,342.1,340,337.9
XS GIS Cut Line= 4
     1697061.735      169417.955     1697310.829       169453.54
     1697553.454       169427.66     1697851.073      169411.485
#Sta/Elev= 30
    10.1 1312.54    40.3 1311.12    50.3 1310.07   130.8 1299.46     161 1293.65
   181.2 1288.67   191.2 1285.74   211.4 1278.46   221.4 1275.53   231.5 1273.48
   261.4 1268.65   300.4  1263.6   329.7 1258.34   334.5 1258.14   339.5 1257.93
   344.5 1258.38     359 1260.47   368.7 1262.81   417.5 1276.47   456.6 1286.16
   485.9 1294.57   525.4 1307.53   535.4 1311.48   555.2 1320.87   604.9 1349.73
   634.7 1365.23   684.4  1389.7   714.2 1403.01   753.9 1418.25   793.7 1435.35
#Mann= 3 , 0 , 0
       0     .06       0   334.5    .045       0   344.5     .06       0
Bank Sta=334.5,344.5
XS Rating Curve= 0 ,0
Exp/Cntr=0.3,0.1

Type RM Length L Ch R = 1 ,12219.1 ,249.1,247.9,246.6
XS GIS Cut Line= 4
     1697029.341      169882.027     1697362.589      169784.173
     1697614.737      169733.507     1697927.043       169706.99
#Sta/Elev= 30
     9.9 1497.21    59.5 1469.39   148.9 1421.16   158.8 1415.21   168.7 1408.54
   198.5 1387.26   287.8 1322.16   297.7  1315.5   307.6 1309.99   347.3  1293.6
   406.7 1264.34   416.6 1260.15   426.5 1257.48   456.1 1252.16     461 1251.65
     466 1251.12     471 1251.41   475.9 1251.69   485.8 1254.17   564.9 1285.83
   614.6 1304.83   665.2 1326.55   685.4 1336.92   705.6    1348   725.8 1359.72
   746.1 1372.24   766.3 1385.58   806.7 1413.95   877.5 1465.43   917.9 1493.34
#Mann= 3 , 0 , 0
       0     .06       0     461    .045       0     471     .06       0
Bank Sta=461,471
XS Rating Curve= 0 ,0
Exp/Cntr=0.3,0.1

Type RM Length L Ch R = 1 ,11971.2 ,229,230.6,232.3
XS GIS Cut Line= 4
     1697107.024      170072.088     1697420.819      170030.033
     1697699.028      169955.628     1697980.473      169952.393
#Sta/Elev= 30
     9.9  1448.7    39.6 1428.79   108.8  1387.5   158.3 1356.34   197.9 1330.73
   217.7 1318.95   237.4 1309.53   267.1 1298.05   286.9 1292.13   306.7 1287.49
   326.5  1282.1   356.3 1271.95   376.2 1263.65     396 1253.74     406 1249.67
   410.9  1248.9   415.9 1248.11   420.9 1248.56   425.8    1249   445.7 1254.68
   564.9  1298.2   604.6 1314.02   634.7 1327.81   664.9 1343.68     685 1355.39
   715.2 1374.36   765.4 1406.92   805.6  1431.7   845.8 1454.84     886 1476.67
#Mann= 3 , 0 , 0
       0     .06       0   410.9    .045       0   420.9     .06       0
Bank Sta=410.9,420.9
XS Rating Curve= 0 ,0
Exp/Cntr=0.3,0.1

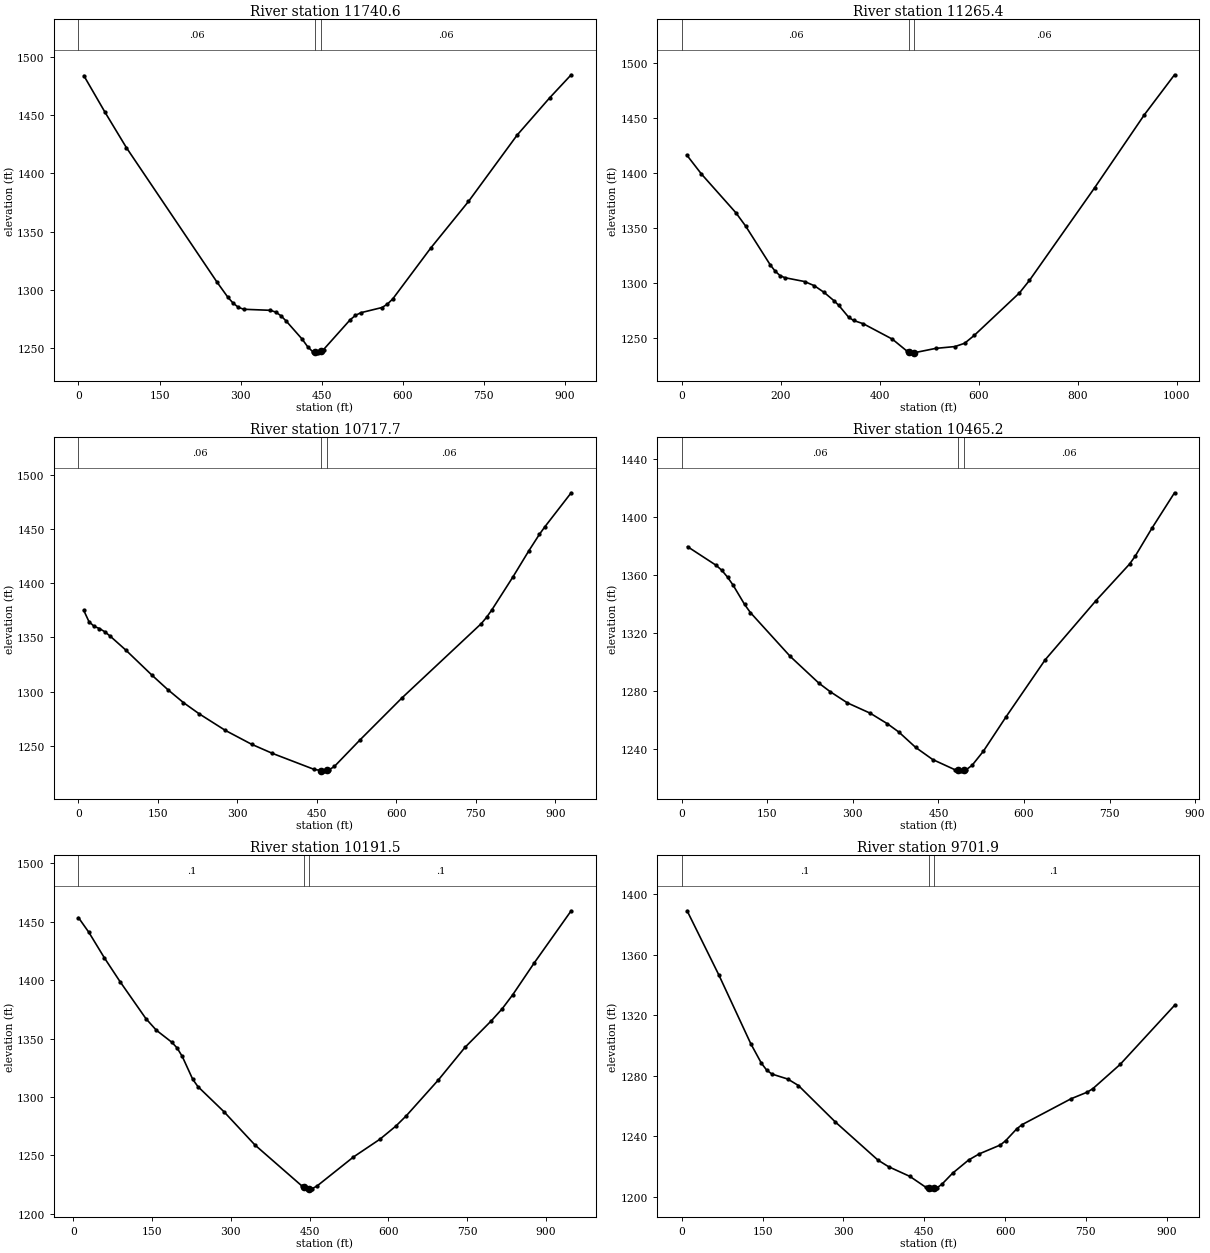
Type RM Length L Ch R = 1 ,11740.6 ,476.1,475.2,474
XS GIS Cut Line= 4
     1697149.424       170318.09     1697466.109      170243.542
     1697708.495       170200.37     1698041.107      170129.485
#Sta/Elev= 30
     9.9  1483.9    49.3 1452.33    88.7 1422.11   256.3 1306.79     276 1294.06
   285.9 1288.85   295.8 1285.19   305.6  1283.5   354.9  1282.6   364.7 1281.14
   374.6 1277.93   384.4 1273.34     414 1257.79   423.8 1251.51   433.7 1246.93
   438.5 1246.53   443.5 1246.12   448.5 1247.54   453.4 1248.92   502.6 1274.45
   512.5 1278.24   522.3 1280.53   561.7 1285.01   571.5  1287.9   581.5 1292.39
   651.6 1335.93   721.6 1375.97   811.6 1432.92   871.6 1464.78   911.6 1484.65
#Mann= 3 , 0 , 0
       0     .06       0   438.5    .045       0   448.5     .06       0
Bank Sta=438.5,448.5
XS Rating Curve= 0 ,0
Exp/Cntr=0.3,0.1

Type RM Length L Ch R = 1 ,11265.4 ,569.7,547.7,525.9
XS GIS Cut Line= 4
     1697275.796      170950.651     1697540.513      170696.441
     1697747.715      170641.745     1698112.097      170444.186
#Sta/Elev= 30
     9.9 1416.61    39.7 1399.26   109.1 1364.17     129 1351.98   178.5 1316.87
   188.5 1311.08   198.4 1306.99   208.3 1305.06     248 1301.58   267.8 1297.77
   287.7 1291.65   307.5 1284.15   317.4 1279.84   337.3 1269.08   347.2 1266.18
     367 1263.16   425.5 1249.21   454.7 1238.47   459.4 1237.64   464.4 1236.76
   469.4 1236.81   513.1  1240.8   552.1 1242.47   571.6 1245.45   591.4 1252.76
   682.4 1291.24   702.6  1302.6   834.1 1386.63   935.1  1453.3   995.8 1489.49
#Mann= 3 , 0 , 0
       0     .06       0   459.4    .045       0   469.4     .06       0
Bank Sta=459.4,469.4
XS Rating Curve= 0 ,0
Exp/Cntr=0.3,0.1

Type RM Length L Ch R = 1 ,10717.7 ,257,252.5,248
XS GIS Cut Line= 4
     1697893.128        171395.2     1698025.763      171074.935
     1698083.982      170848.481     1698219.783      170526.283
#Sta/Elev= 30
     9.9 1374.82    19.8  1364.4    29.7 1360.04    39.6 1358.06    49.5 1355.14
    59.4 1351.25    89.1 1338.32   138.7  1315.1   168.4 1301.88   198.1 1289.83
   227.8  1279.5   277.3 1264.19   326.8 1251.43   366.1 1243.04   444.1 1228.42
   458.6 1227.07   463.6 1226.95   468.6 1227.47   473.3 1227.97     483 1230.95
   531.7 1255.58   610.4 1294.03   760.3 1362.57   770.3 1368.35   780.3 1375.22
   820.2 1405.67   850.2 1429.73   870.2 1444.93   880.2 1451.69   930.1 1483.16
#Mann= 3 , 0 , 0
       0     .06       0   458.6    .045       0   468.6     .06       0
Bank Sta=458.6,468.6
XS Rating Curve= 0 ,0
Exp/Cntr=0.3,0.1

Type RM Length L Ch R = 1 ,10465.2 ,280.9,273.8,266.6
XS GIS Cut Line= 4
     1698126.047      171443.725     1698297.502       171104.05
     1698303.972      170916.421     1698355.732      170625.271
#Sta/Elev= 30
      10 1379.33    60.1  1366.5    70.1 1363.03    80.1 1358.37    90.1 1352.68
   110.1 1339.51   120.2 1333.94   190.2 1303.68   240.3 1285.31   260.3 1279.39
   290.4 1271.69   330.4 1264.58   360.5 1257.32   380.5 1251.63   410.1    1241
   439.8  1232.7   479.3 1225.58   484.2 1225.24   489.2 1224.89   494.2 1225.35
   499.1  1225.8   508.9 1228.67   528.7 1238.38   568.2 1261.92   637.2 1301.43
   725.9 1342.01   785.1 1367.35   794.9 1372.74   824.5 1392.16   863.9 1416.44
#Mann= 3 , 0 , 0
       0     .06       0   484.2    .045       0   494.2     .06       0
Bank Sta=484.2,494.2
XS Rating Curve= 0 ,0
Exp/Cntr=0.3,0.1

Type RM Length L Ch R = 1 ,10191.5 ,485.4,489.5,493.7
XS GIS Cut Line= 4
     1698590.326      171475.484     1698604.826       171129.93
     1698543.361      170942.301      1698408.02      170561.023
#Sta/Elev= 30
     9.9 1453.58    29.6 1441.05    59.3 1419.09    88.9 1398.87   138.3 1367.08
   158.1 1357.19   187.8 1346.81   197.6    1342   207.5 1334.72   227.3 1315.25
   237.2 1308.95   286.6 1287.52   345.9 1258.89   434.7 1224.03   439.6 1222.74
  444.59 1221.35   449.6 1221.42   454.5 1221.43   464.3 1223.87   533.4 1248.63
   583.8 1263.85   614.1 1275.08   634.3 1284.07     695 1314.57   745.6 1342.44
   796.2 1365.42   816.4 1375.47   836.6 1387.54   877.1 1414.53   947.9 1459.47
#Mann= 3 , 0 , 0
     9.9      .1       0   439.6    .045       0   449.6      .1       0
Bank Sta=439.6,449.6
XS Rating Curve= 0 ,0
Exp/Cntr=0.3,0.1

Type RM Length L Ch R = 1 ,9701.9  ,252.4,258.9,265.4
XS GIS Cut Line= 4
     1699001.776      171315.393     1699018.905      170961.711
     1698993.025      170715.851     1698942.918      170406.846
#Sta/Elev= 30
     9.8 1389.04    68.9 1346.44   127.9 1301.16   147.5  1288.3   157.4 1283.66
   167.2 1281.02   196.7 1277.71   216.4 1273.44   285.2 1249.22     364  1224.1
   383.8 1219.71   423.3  1213.3     453 1206.08   457.9 1205.58   462.9 1205.08
   467.9 1205.32   472.8 1205.56   482.6 1208.09   502.4 1215.38   532.1 1224.11
   551.9 1228.19   591.4 1234.13   601.3 1237.04   621.5 1244.75   631.6 1247.57
   722.5 1264.69   752.8  1269.1   762.9 1271.37   813.4 1287.36   914.4 1326.45
#Mann= 3 , 0 , 0
       0      .1       0   457.9    .045       0   467.9      .1       0
Bank Sta=457.9,467.9
XS Rating Curve= 0 ,0
Exp/Cntr=0.3,0.1

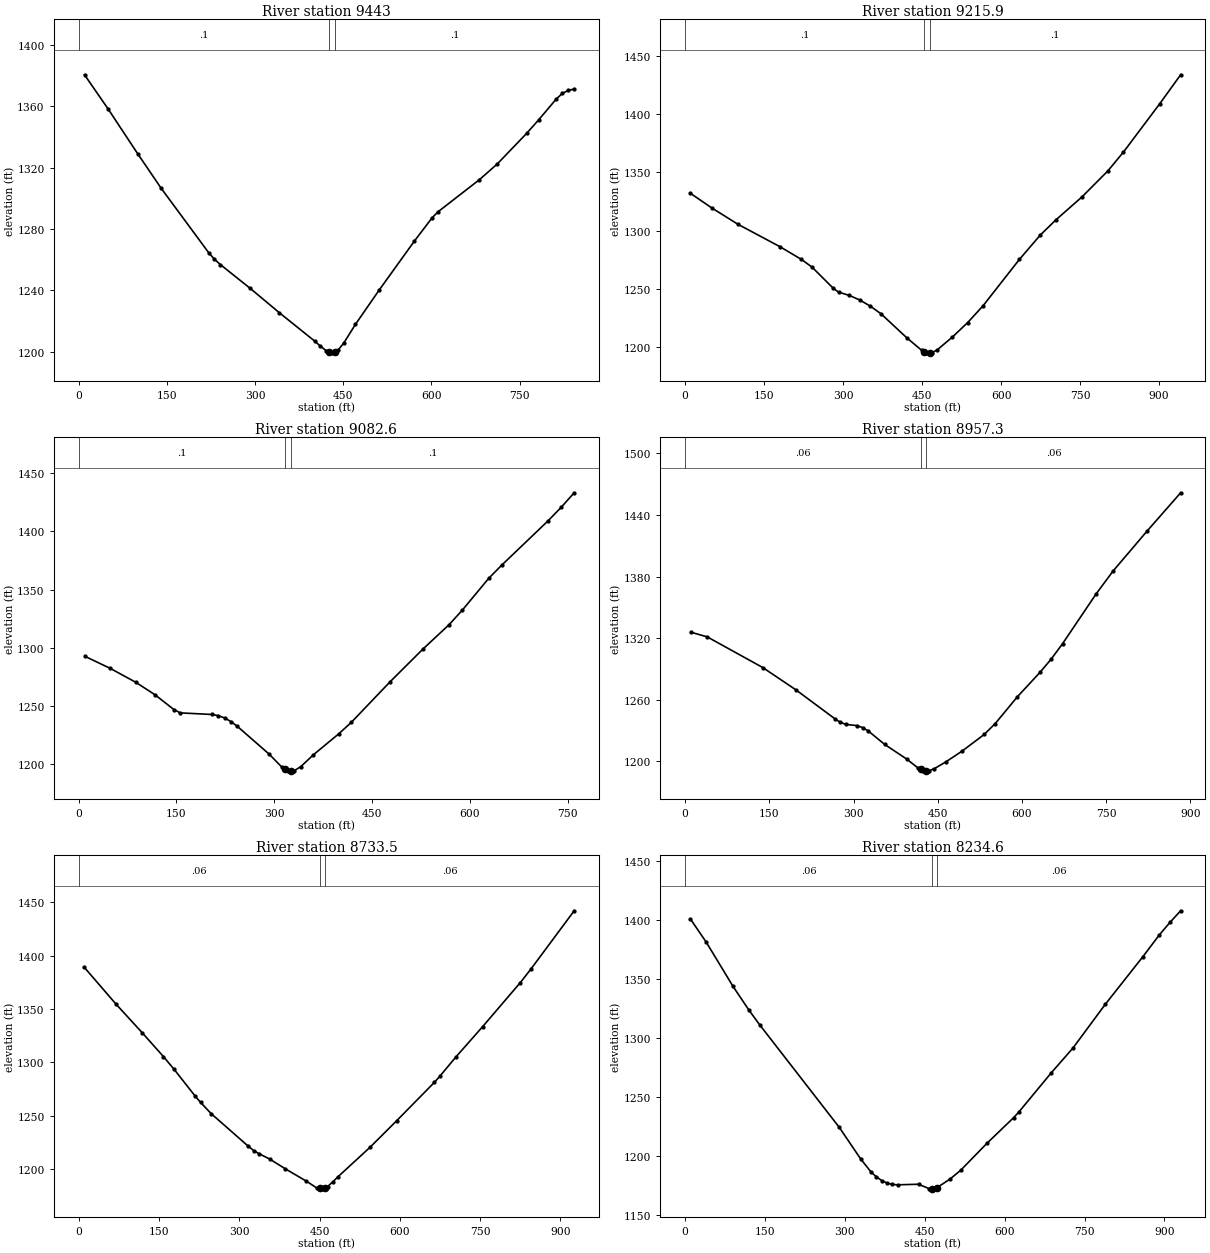
Type RM Length L Ch R = 1 ,9443    ,239.9,227.1,214.3
XS GIS Cut Line= 4
     1699154.775      171294.915     1699245.355      170955.241
     1699284.175      170780.551     1699251.825      170469.992
#Sta/Elev= 30
      10 1380.56    50.2 1358.23   100.4 1329.06   140.6 1306.38     221 1264.55
     231 1260.18   241.1  1256.7   291.3 1241.34   341.5 1225.25   401.3 1206.83
   411.2 1203.49   421.1 1200.48   426.1  1199.8   431.1 1199.13   436.1 1199.98
     441  1200.8     451 1205.58   470.8 1217.76   510.6 1239.82   570.8 1271.96
     601 1287.18   611.1 1291.14   681.6 1312.13   711.8 1322.33   762.2 1342.46
   782.3 1351.15   812.5 1364.87   822.6 1368.37   832.7 1370.35   842.7 1371.28
#Mann= 3 , 0 , 0
       0      .1       0   426.1    .045       0   436.1      .1       0
Bank Sta=426.1,436.1
XS Rating Curve= 0 ,0
Exp/Cntr=0.3,0.1

Type RM Length L Ch R = 1 ,9215.9  ,119,133.3,147.6
XS GIS Cut Line= 4
     1699527.532      171356.103     1699513.859      170974.651
     1699439.454      170806.431     1699413.648      170432.084
#Sta/Elev= 30
      10 1332.12    50.2 1319.64   100.4 1305.44   180.8 1286.02     221 1275.19
   241.1  1268.6   281.3 1250.46   291.3 1247.13   311.4 1244.37   331.5 1240.41
   351.6 1235.09   371.7 1228.61   420.4 1208.08   449.5 1196.98   454.1    1196
   459.1 1194.94   464.1 1195.04   468.8 1195.13   478.5  1197.4   507.6 1208.54
   536.6 1220.98   565.6 1235.32   634.8 1275.29   674.3 1296.13   703.9 1309.18
   753.3 1328.87   802.6 1351.28   832.3 1367.51   901.4 1409.18   940.9 1433.97
#Mann= 3 , 0 , 0
       0      .1       0   454.1    .045       0   464.1      .1       0
Bank Sta=454.1,464.1
XS Rating Curve= 0 ,0
Exp/Cntr=0.3,0.1

Type RM Length L Ch R = 1 ,9082.6  ,127.3,125.3,123.2
XS GIS Cut Line= 4
     1699559.149       171220.51     1699581.794      170958.476
     1699630.319      170780.551     1699594.734      170469.992
#Sta/Elev= 30
     9.7 1292.63    48.7 1282.21    87.7 1270.31   116.9 1259.67   146.1 1246.92
   155.9 1244.03   204.6 1242.66   214.3 1241.63     224 1239.64   233.8 1236.51
   243.5 1232.41   292.1 1208.63   311.5 1197.54   316.2 1195.93   321.2 1194.23
   326.2 1194.33     331 1194.43   340.7 1197.83   360.1 1208.05   398.9    1226
   418.3 1235.93   477.7 1270.77   528.1 1298.91   568.4 1319.96   588.6 1332.42
   628.9 1359.63   649.1 1371.11   719.7 1408.93   739.9 1420.58     760 1433.18
#Mann= 3 , 0 , 0
       0      .1       0   316.2    .045       0   326.2      .1       0
Bank Sta=316.2,326.2
XS Rating Curve= 0 ,0
Exp/Cntr=0.3,0.1

Type RM Length L Ch R = 1 ,8957.3  ,226.2,223.8,221.5
XS GIS Cut Line= 4
     1699575.324        171330.5     1699707.959      171000.531
     1699743.544      170787.021     1699746.779      170476.462
#Sta/Elev= 30
     9.9 1325.79    39.5 1321.13   138.3 1291.27   197.6 1269.43   266.7 1241.33
   276.6 1237.85   286.5 1235.81   306.2 1234.62   316.1 1232.68     326 1229.53
   355.6 1216.24     395 1201.91   414.7 1193.39   419.5 1191.99   424.5 1190.52
   429.5 1190.53   434.3 1190.54   444.2 1192.74   463.9 1199.05   493.4 1209.75
   532.7 1225.97   552.4  1236.6   592.1 1262.88   632.2 1286.56   652.2 1299.56
   672.3 1314.45   732.4 1363.27   762.4  1385.4   822.5 1424.09   882.7 1461.68
#Mann= 3 , 0 , 0
       0     .06       0   419.5    .045       0   429.5     .06       0
Bank Sta=419.5,429.5
XS Rating Curve= 0 ,0
Exp/Cntr=0.3,0.1

Type RM Length L Ch R = 1 ,8733.5  ,501.7,498.9,496.1
XS GIS Cut Line= 4
     1699841.998      171395.077     1699934.408      171081.405
     1699944.113      170864.661     1699945.106      170482.936
#Sta/Elev= 30
     9.9 1389.32    69.4 1354.72   118.9 1327.58   158.5 1305.27   178.4 1293.35
     218 1268.07   227.9 1262.32   247.7 1251.79   317.1 1221.23     327 1217.28
   336.9 1214.32   356.6 1209.39   386.2 1200.12   425.6 1188.49   445.3 1182.06
   450.2 1181.72   455.2 1181.38   460.2 1182.47   465.1 1183.55   474.9 1187.95
   484.8 1192.85     544 1220.15   594.2 1245.25   664.5 1281.11   674.6  1286.8
   704.7 1304.94   754.9 1333.47   825.2 1374.71   845.3 1387.59   925.7 1441.94
#Mann= 3 , 0 , 0
       0     .06       0   450.2    .045       0   460.2     .06       0
Bank Sta=450.2,460.2
XS Rating Curve= 0 ,0
Exp/Cntr=0.3,0.1

Type RM Length L Ch R = 1 ,8234.6  ,491.3,511.7,532.2
XS GIS Cut Line= 4
     1700357.409      171462.188     1700429.362      171120.225
     1700406.717      170884.071     1700451.371      170543.149
#Sta/Elev= 30
      10 1400.77    39.9 1380.99    89.9  1343.7   119.8 1323.57   139.8 1311.22
   289.5 1224.14   329.5 1197.51   349.5  1186.1   359.3 1182.15   369.2 1179.09
   379.1 1176.95     389 1175.74   398.9 1175.45   438.4 1175.92   458.2  1172.2
   463.1 1172.12   468.1 1172.03   473.1 1173.09   497.7 1180.38   517.5 1187.78
   566.9 1210.67     617 1232.42   627.1 1237.38   687.8 1270.49   728.3 1291.38
   788.9 1328.39   859.7 1368.87   890.1 1387.05   910.3 1397.82   930.5 1407.73
#Mann= 3 , 0 , 0
       0     .06       0   463.1    .045       0   473.1     .06       0
Bank Sta=463.1,473.1
XS Rating Curve= 0 ,0
Exp/Cntr=0.3,0.1

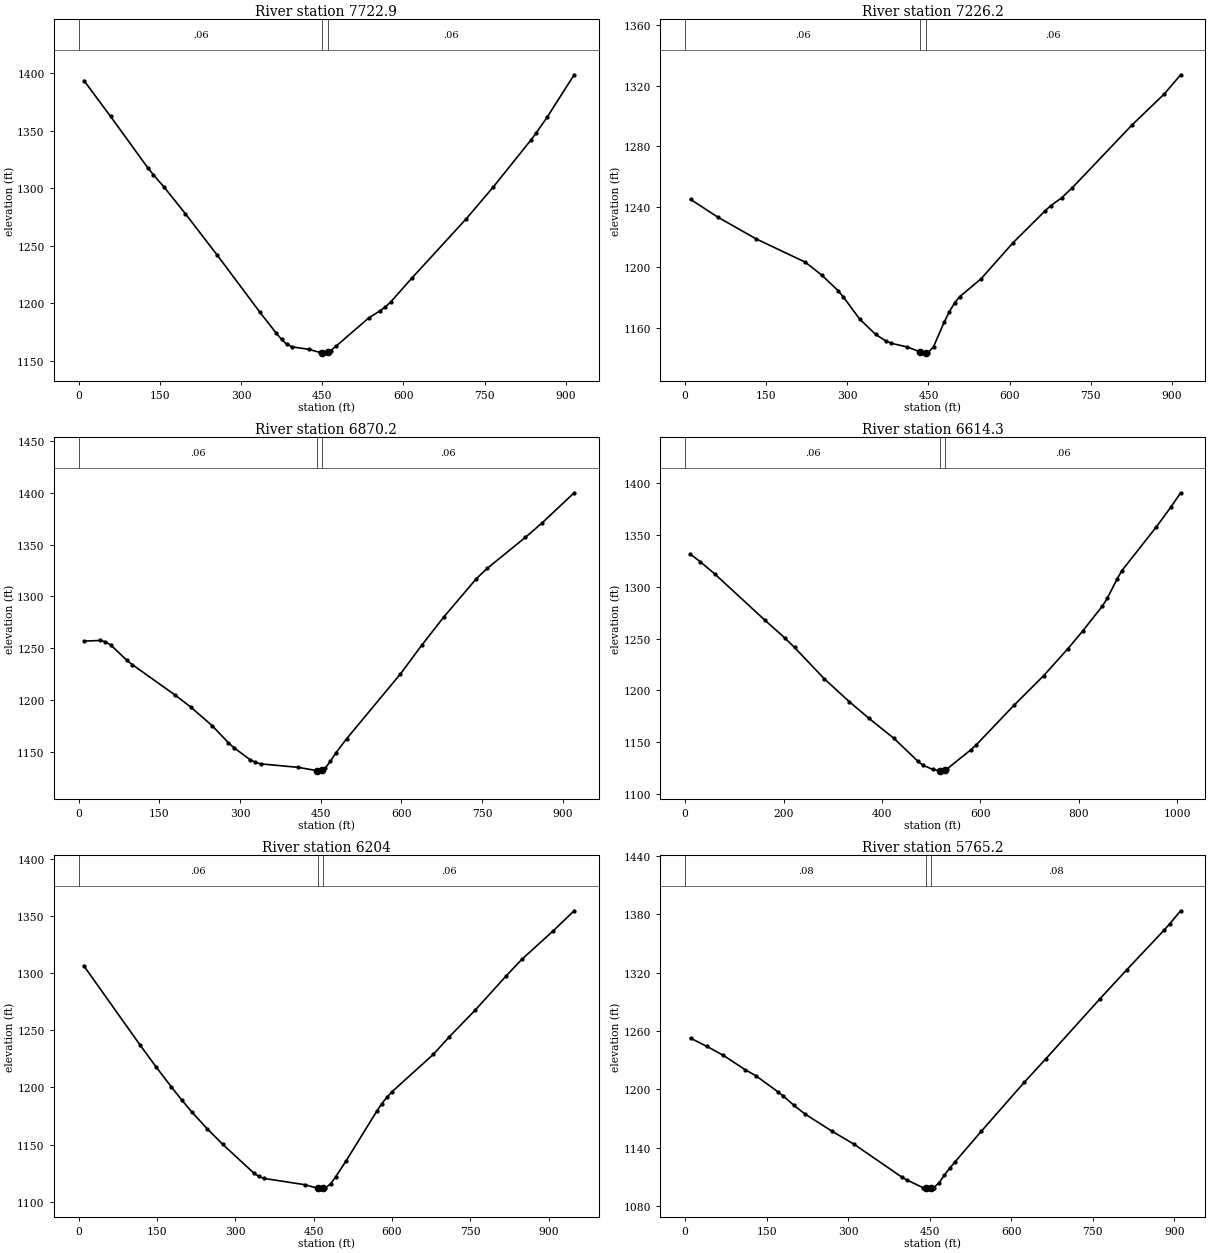
Type RM Length L Ch R = 1 ,7722.9  ,498.9,496.7,494.5
XS GIS Cut Line= 4
     1700478.397      171526.784     1700749.627       171298.15
     1700950.196      171146.105     1701183.887      170943.917
#Sta/Elev= 30
     9.9  1393.6    59.1  1362.4   128.1 1317.59     138 1311.77   157.7 1301.14
   197.1 1277.94   256.2 1241.83     335 1192.16   364.8 1174.26   374.9 1168.62
   384.9 1164.31     395 1162.11   425.2 1160.06   445.3 1157.39   450.4 1157.19
   455.4 1156.99   460.4 1157.98   465.5 1158.99   475.5 1162.78     536 1187.36
   556.1 1193.32   566.2 1196.75   576.2 1201.04   616.4 1222.38   716.1 1273.54
   765.9  1301.1   835.7 1342.06   845.7 1348.36   865.6 1361.94   915.4 1398.66
#Mann= 3 , 0 , 0
       0     .06       0   450.4    .045       0   460.4     .06       0
Bank Sta=450.4,460.4
XS Rating Curve= 0 ,0
Exp/Cntr=0.3,0.1

Type RM Length L Ch R = 1 ,7226.2  ,350.3,356,361.7
XS GIS Cut Line= 4
     1700917.063      171925.015     1701102.241      171660.469
     1701293.105       171479.31     1701513.165      171233.214
#Sta/Elev= 30
    10.1 1244.88    60.5 1233.16   131.2 1218.86     222 1203.49   252.3 1195.04
   282.6 1184.77   292.6 1180.51   322.9 1165.88   352.2 1155.81   371.6 1151.44
   381.4 1149.94   410.6 1147.51   434.9 1144.28   439.9 1143.65   444.9  1143.7
   449.6 1143.75   459.4 1147.77   478.9  1163.8   488.6 1170.75   498.4 1176.66
   508.1  1180.8   547.1 1192.46   606.1 1216.19   666.1 1237.49   676.1 1240.76
   696.1 1245.85   716.1 1252.64   826.2 1293.92   886.2 1314.52   916.2 1327.08
#Mann= 3 , 0 , 0
       0     .06       0   434.9    .045       0   444.9     .06       0
Bank Sta=434.9,444.9
XS Rating Curve= 0 ,0
Exp/Cntr=0.3,0.1

Type RM Length L Ch R = 1 ,6870.2  ,265,255.9,246.8
XS GIS Cut Line= 4
     1701001.956      172009.848     1701338.395      171886.919
     1701551.905      171776.929     1701710.419      171495.485
#Sta/Elev= 30
     9.9 1256.98    39.8 1257.58    49.7  1256.4    59.7 1253.21    89.5 1238.56
    99.5 1234.41   179.1 1205.11   208.9 1193.25   248.7 1175.24   278.6 1158.96
   288.5 1154.34   318.4 1142.84   328.3  1140.2   338.3 1138.67   408.2  1135.3
   443.3 1132.11   448.3 1131.94   453.3 1133.17   458.3 1134.41   468.3 1141.28
   478.3 1149.25   498.3 1162.86   598.4 1225.38   638.7 1253.53   679.1 1280.29
   739.7 1317.27   759.9 1327.15   830.5 1356.93   860.8 1370.45   921.4 1399.96
#Mann= 3 , 0 , 0
       0     .06       0   443.3    .045       0   453.3     .06       0
Bank Sta=443.3,453.3
XS Rating Curve= 0 ,0
Exp/Cntr=0.3,0.1

Type RM Length L Ch R = 1 ,6614.3  ,407.4,410.3,413.1
XS GIS Cut Line= 4
     1701089.807      172162.612     1701513.085      172129.543
      1701665.13      171925.739     1701849.103      171654.163
#Sta/Elev= 30
    10.1  1331.8    30.3 1324.43    60.7 1312.28   161.7 1267.97   202.2 1250.82
   222.4 1241.43     283 1211.06   333.6 1189.04     374 1172.81   424.6  1153.5
   473.5 1131.28   483.2 1127.68   502.8 1123.66   517.4 1122.31   522.4 1122.23
   527.4 1123.16   532.1 1124.03     581  1142.7   590.8 1146.93   669.1 1185.96
   728.5 1214.15   778.2  1240.4   808.1 1257.47   847.8 1281.38   857.8 1288.91
   877.6 1307.41   887.6 1315.68   957.2 1357.71     987 1377.05  1006.9 1390.87
#Mann= 3 , 0 , 0
       0     .06       0   517.4    .045       0   527.4     .06       0
Bank Sta=517.4,527.4
XS Rating Curve= 0 ,0
Exp/Cntr=0.3,0.1

Type RM Length L Ch R = 1 ,6204    ,439.3,438.7,438.1
XS GIS Cut Line= 4
     1701583.306      172566.405     1701852.759      172320.408
     1702046.859      172126.308     1702159.002      171837.557
#Sta/Elev= 30
     9.9  1306.7   118.3 1236.81   147.9 1218.29   177.5 1200.52   197.2 1189.18
   216.9 1178.44   246.5 1163.68   276.1 1150.09   335.3 1125.06   345.1 1122.01
     355 1120.28   433.5 1114.75   457.9 1111.61   462.9 1111.14   467.9 1111.56
   472.7 1111.96   482.5 1115.51   492.3 1121.69   511.9 1135.38   570.7    1179
   580.5 1185.69   590.3 1191.39   600.1 1196.21   679.3    1229   709.3 1244.09
   759.3 1267.69   819.2 1297.96   849.2 1312.46   909.1 1337.39   949.1 1354.89
#Mann= 3 , 0 , 0
       0     .06       0   457.9    .045       0   467.9     .06       0
Bank Sta=457.9,467.9
XS Rating Curve= 0 ,0
Exp/Cntr=0.3,0.1

Type RM Length L Ch R = 1 ,5765.2  ,509,507.1,505.2
XS GIS Cut Line= 4
     1701920.205      172952.531     1702114.794      172673.022
     1702275.224      172503.186     1702493.153      172245.292
#Sta/Elev= 30
      10 1252.63    40.1 1244.24    70.1 1235.12   110.2 1220.43   130.2 1214.06
   170.3 1197.81   180.3 1193.44   200.3 1183.66   220.4 1174.84   270.5 1157.04
   310.5 1143.87     399 1109.87   408.7 1106.84   437.9 1099.04   442.7 1098.48
   447.7 1097.89   452.7 1098.48   457.4 1099.02   467.1 1104.06   476.9 1111.81
   486.6 1118.92   496.3 1125.36     545 1157.02   623.9 1207.22   663.6 1231.39
   762.9 1292.85   812.5 1322.85   882.1 1364.15     892 1370.38   911.8 1383.57
#Mann= 3 , 0 , 0
       0     .08       0   442.7    .045       0   452.7     .08       0
Bank Sta=442.7,452.7
XS Rating Curve= 0 ,0
Exp/Cntr=0.3,0.1

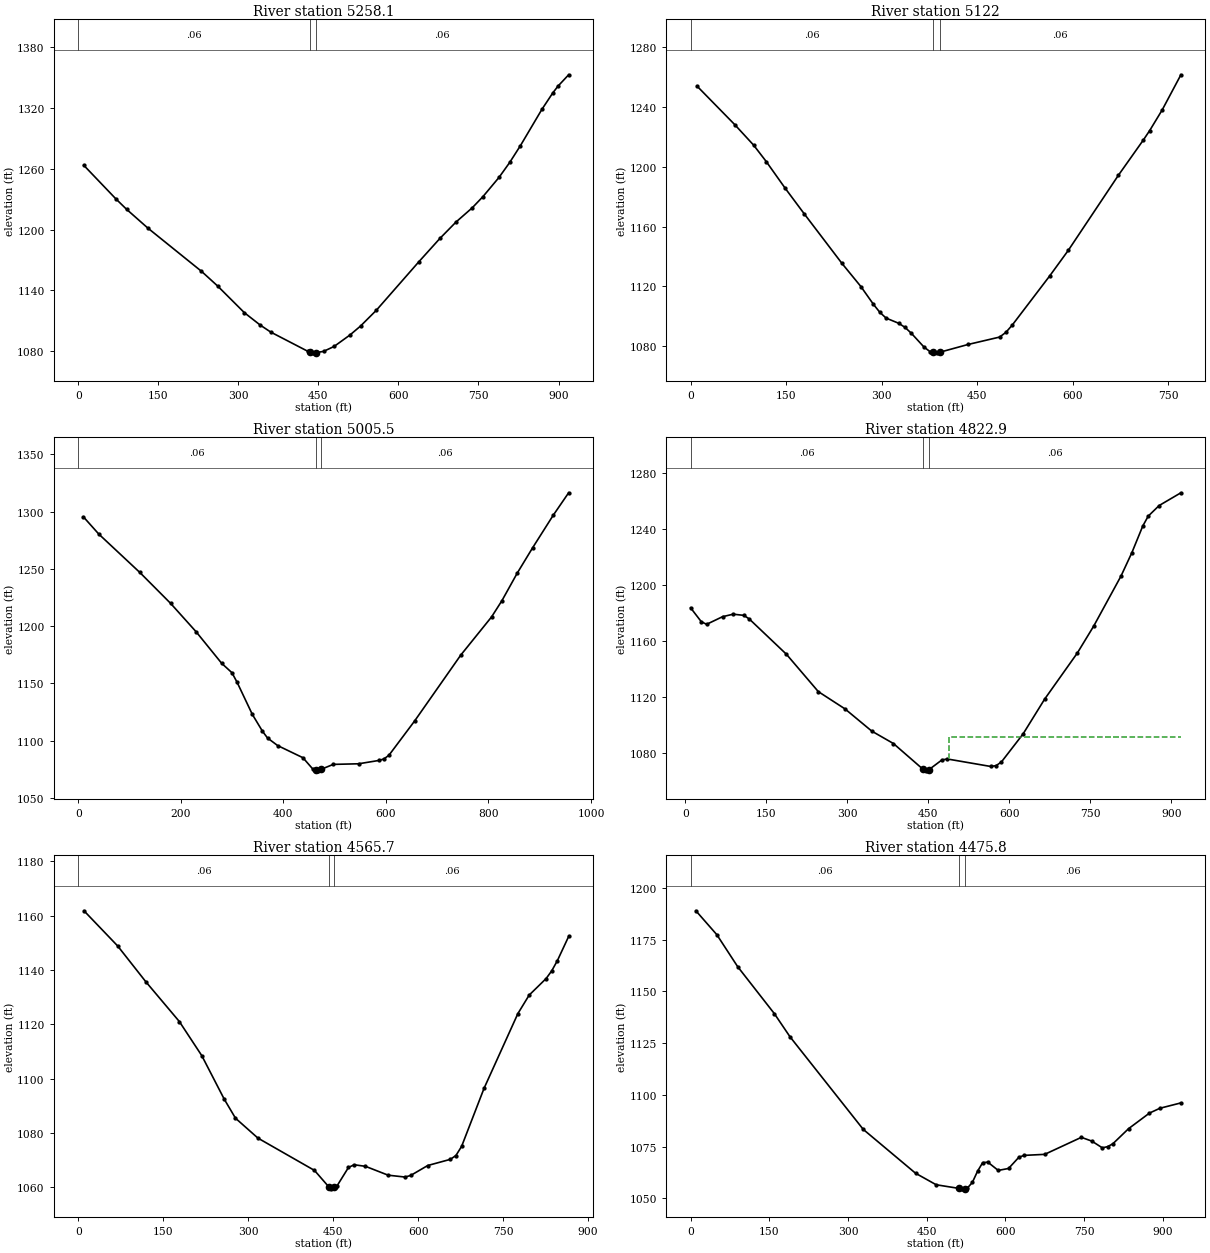
Type RM Length L Ch R = 1 ,5258.1  ,139.4,136.2,132.9
XS GIS Cut Line= 4
     1702257.283      173212.279     1702506.228      173009.461
     1702695.602       172768.24     1702878.127      172541.281
#Sta/Elev= 30
      10 1263.46    70.2 1230.32    90.3 1220.02   130.4 1201.38   230.8  1158.8
   260.9 1144.38   311.1 1118.02   340.9 1105.75   360.7 1098.82   429.9 1079.95
   434.8 1079.18   439.8 1078.38   444.8  1078.5   459.6 1079.82   479.4  1084.7
   509.1 1095.98   528.9  1104.8   558.5 1120.35   637.8 1167.97     678 1191.42
   708.1 1207.53   738.3 1221.45   758.3 1232.45   788.5 1251.44   808.6 1266.24
   828.6 1282.75   868.8  1318.5   888.9 1334.49   898.9  1341.4     919 1352.68
#Mann= 3 , 0 , 0
       0     .06       0   434.8    .045       0   444.8     .06       0
Bank Sta=434.8,444.8
XS Rating Curve= 0 ,0
Exp/Cntr=0.3,0.1

Type RM Length L Ch R = 1 ,5122    ,124.4,116.4,108.5
XS GIS Cut Line= 4
     1702405.084      173245.937     1702629.408      173100.429
     1702730.455      172918.545     1702841.606      172645.719
#Sta/Elev= 30
     9.9 1253.97    69.3 1228.14      99  1214.4   118.8 1203.43   148.5  1185.6
   178.3 1168.56   237.7 1135.32   267.4 1119.86   287.2 1107.91   297.1 1102.65
     307 1098.75   326.8 1095.29   336.7 1092.56   346.6 1088.63   366.5  1079.4
   376.4 1076.19   381.3 1075.86   386.3 1075.52   391.3 1075.92   435.8 1081.12
   485.3 1086.07   495.1 1089.21   504.9 1093.96   563.8 1126.88   593.3 1144.15
   671.9 1194.32   711.1 1217.91     721 1224.19   740.6 1237.96     770 1261.48
#Mann= 3 , 0 , 0
       0     .06       0   381.3    .045       0   391.3     .06       0
Bank Sta=381.3,391.3
XS Rating Curve= 0 ,0
Exp/Cntr=0.3,0.1

Type RM Length L Ch R = 1 ,5005.5  ,183.5,182.6,181.8
XS GIS Cut Line= 4
     1702506.228      173355.606     1702777.967      173187.386
     1702810.317      172893.001     1702942.952      172579.207
#Sta/Elev= 30
      10 1295.36    39.9 1280.38   119.8 1246.92   179.8 1219.95   229.7 1195.08
   279.6  1167.5   299.6 1159.31   309.6    1151   339.3 1122.95   359.1 1108.23
     369 1102.29   388.7  1095.7   438.1 1085.06   457.8 1074.94   462.7 1074.29
   467.7 1073.61   472.7  1074.8   497.3 1079.25   546.6 1079.77   586.1 1082.67
     596 1083.98   605.9 1087.25   655.8 1117.07     746 1174.73   806.1 1208.09
   826.2  1222.2   856.2 1246.37   886.3 1268.57   926.4  1296.9   956.4 1316.48
#Mann= 3 , 0 , 0
       0     .06       0   462.7    .045       0   472.7     .06       0
Bank Sta=462.7,472.7
XS Rating Curve= 0 ,0
Exp/Cntr=0.3,0.1

Type RM Length L Ch R = 1 ,4822.9  ,255.7,257.1,258.5
XS GIS Cut Line= 4
     1702957.837      173502.471     1702965.597      173187.386
     1702988.242      172838.007     1703042.525      172591.663
#Sta/Elev= 30
     9.8 1183.83    29.5 1173.94    39.4 1172.04    68.9  1177.5    88.6 1179.29
   108.3 1178.45   118.2 1175.93   187.1 1150.66   246.2 1123.93   295.5  1111.6
   345.2 1095.68   385.2 1086.83   440.2 1068.36   445.2 1067.29   450.2  1067.9
   475.2 1075.13   485.2 1075.76   565.3 1070.42   575.3 1070.98   585.3 1073.69
   625.3 1093.67   665.3  1118.6   725.8 1151.55   756.1  1170.8   806.6 1206.54
   826.7 1223.25   846.9 1242.32     857  1249.4   877.2 1256.96   917.5 1266.09
#Mann= 3 , 0 , 0
     9.8     .06       0   440.2    .045       0   450.2     .06       0
#XS Ineff= 2 , 0
                          488.83         1091.28
Permanent Ineff=
       F       F
Bank Sta=440.2,450.2
XS Rating Curve= 0 ,0
Exp/Cntr=0.3,0.1

Type RM Length L Ch R = 1 ,4565.7  ,89.3,89.9,90.1
XS GIS Cut Line= 4
     1703003.281      173429.842     1703207.395      173187.329
     1703247.814      172880.147     1703235.688      172641.677
#Sta/Elev= 30
     9.9 1161.81    69.3 1148.87   118.9 1135.72   178.3 1121.01   217.9 1108.45
   257.5 1092.43   277.4 1085.41     317 1078.08   416.9 1066.17   441.9 1060.18
   446.9 1059.39   451.9 1059.97   456.9 1060.55   476.9 1067.27   486.9 1068.26
   506.9 1067.68   546.9 1064.42   576.8 1063.73   586.8 1064.33   616.8 1067.98
   656.7 1070.25   666.6 1071.67   676.6 1075.01   716.3 1096.44     776 1123.95
   795.9 1130.75   825.8 1136.84   835.7 1139.67   845.7 1143.44   865.6 1152.34
#Mann= 3 , 0 , 0
       0     .06       0   441.9    .045       0   451.9     .06       0
Bank Sta=441.9,451.9
XS Rating Curve= 0 ,0
Exp/Cntr=0.3,0.1

Type RM Length L Ch R = 1 ,4475.8  ,150.9,170,189.6
XS GIS Cut Line= 4
     1703010.887       173494.71     1703292.331      173171.211
     1703334.386      172928.586     1703467.021      172705.372
#Sta/Elev= 30
      10 1189.04    49.9 1177.49    89.7    1162   159.6 1139.29   189.5 1128.07
   329.1 1083.29   428.8 1062.08   468.2  1056.5   512.4 1054.71   517.4 1054.53
   522.4 1054.68   527.3 1054.82   537.1 1057.63     547 1063.04   556.8 1067.22
   566.7 1067.42   586.4 1063.45   606.1 1064.38   625.8 1069.81   635.6 1070.71
     675 1071.21   744.9 1079.44   764.9 1077.62   784.9 1074.36   794.9 1074.94
   804.9 1076.31   834.8 1083.61   874.8 1091.18   894.7 1093.51   934.7  1096.1
#Mann= 3 , 0 , 0
       0     .06       0   512.4    .045       0   522.4     .06       0
Bank Sta=512.4,522.4
XS Rating Curve= 0 ,0
Exp/Cntr=0.3,0.1