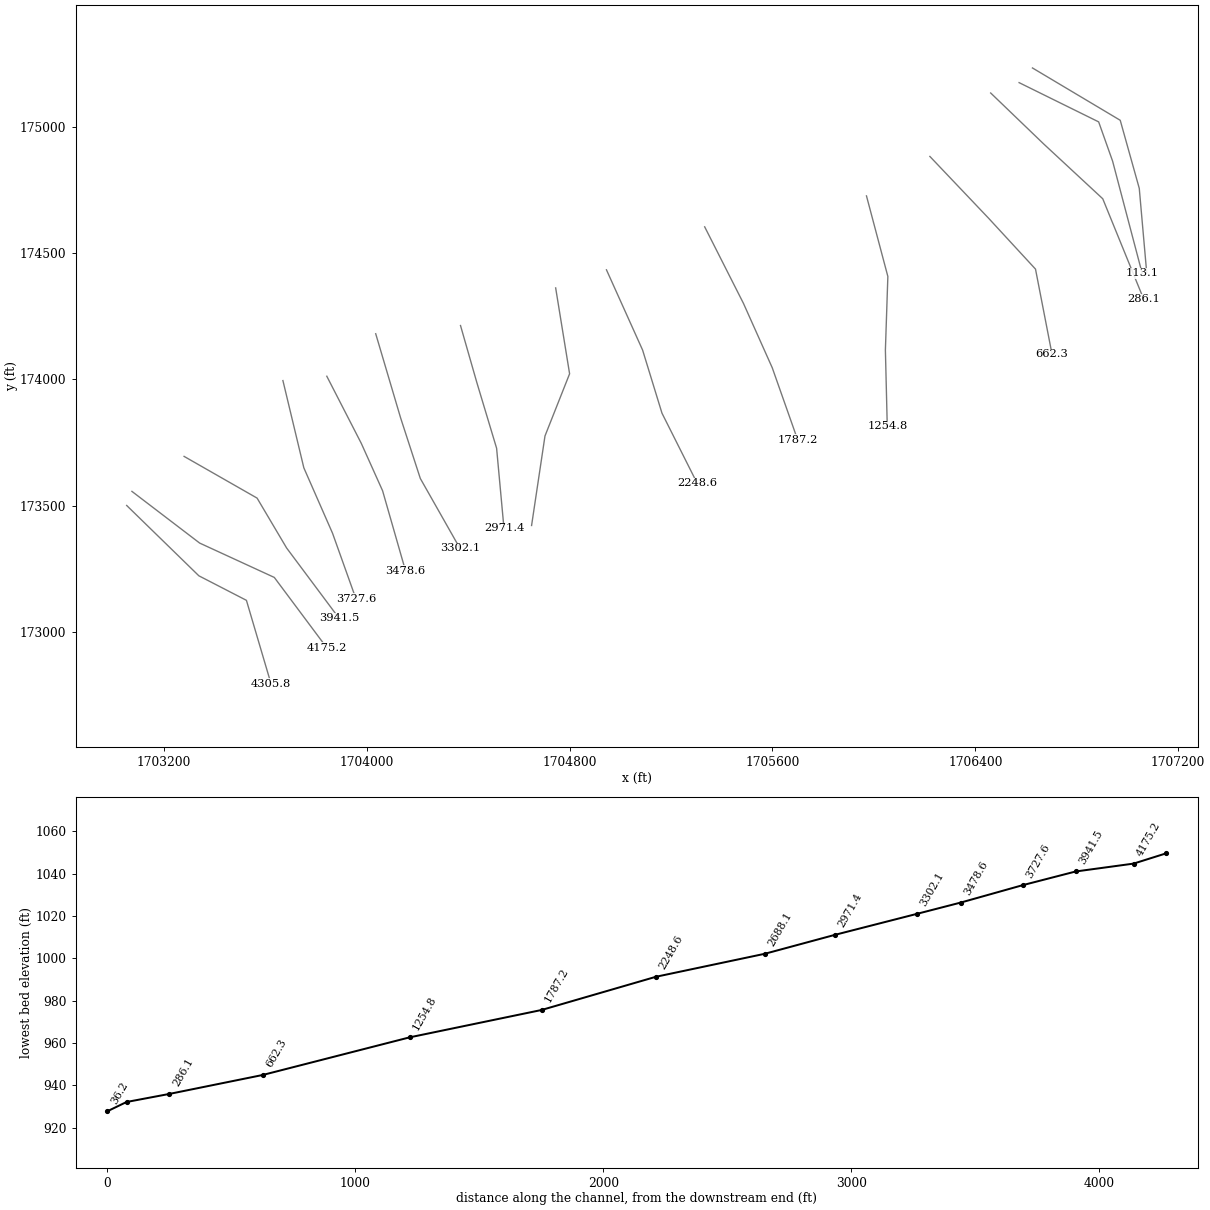
HEC-RAS study Greenbrier Fork.prj: Greenbrier Fork

--- Greenbrier Fork.g01 (geometry) --- (continued)

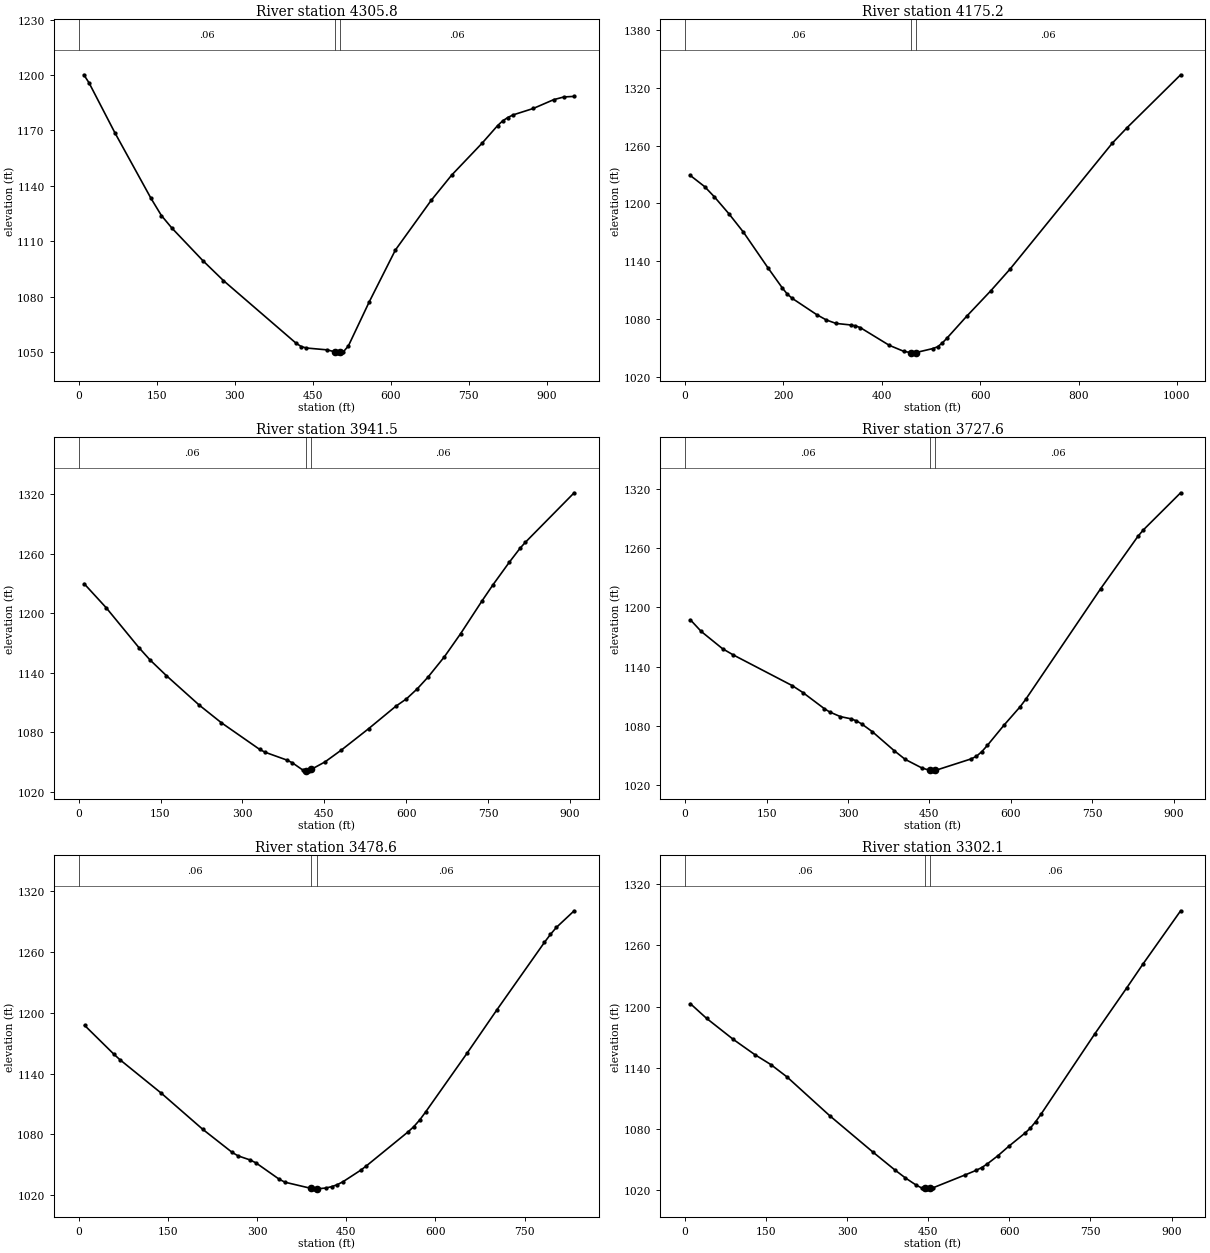
Type RM Length L Ch R = 1 ,4305.8  ,129.7,130.6,131.5
XS GIS Cut Line= 4
     1703052.942       173501.18     1703337.621      173222.971
     1703525.251      173125.921       1703622.3      172795.952
#Sta/Elev= 30
      10 1200.17    19.9 1195.86    69.7 1168.77   139.3 1133.16   159.2 1123.91
   179.1  1117.2   238.8 1099.51   278.6 1088.64   418.2 1054.73   428.2  1052.9
   438.3 1052.11   478.5  1051.1   493.6 1049.96   498.6  1049.5   503.6  1049.7
   508.7 1049.91   518.8  1053.2     559 1077.13   609.3 1105.21   678.1  1132.1
   717.4 1145.76   776.4  1163.2   805.8  1172.6   815.7  1175.2   825.5 1177.01
   835.3 1178.39   874.6 1181.92   913.9  1186.7   933.6 1188.16   953.2 1188.46
#Mann= 3 , 0 , 0
       0     .06       0   493.6    .045       0   503.6     .06       0
Bank Sta=493.6,503.6
XS Rating Curve= 0 ,0
Exp/Cntr=0.3,0.1

Type RM Length L Ch R = 1 ,4175.2  ,245.6,233.6,221.4
XS GIS Cut Line= 4
     1703073.692      173556.866     1703340.856       173352.37
      1703635.24      173216.501      1703842.28      172938.291
#Sta/Elev= 30
     9.9 1229.35    39.6 1217.54    59.4 1206.93    89.1 1189.25   118.7 1170.07
   168.2 1133.26   197.9 1111.97   207.8 1105.76   217.7 1101.36   267.2 1084.52
     287 1078.89   306.8 1075.26   336.4 1073.68   346.3 1072.73   356.1 1070.94
     415 1052.53   444.5 1046.27   459.2 1044.84   464.2 1044.68   469.2 1044.96
   503.5 1049.11   513.3 1050.98   523.1    1055   532.9 1060.23   572.2 1082.55
   621.4 1109.14   660.7 1131.77   868.7 1262.74   898.5 1278.72  1007.5 1333.75
#Mann= 3 , 0 , 0
       0     .06       0   459.2    .045       0   469.2     .06       0
Bank Sta=459.2,469.2
XS Rating Curve= 0 ,0
Exp/Cntr=0.3,0.1

Type RM Length L Ch R = 1 ,3941.5  ,217.2,213.9,210.8
XS GIS Cut Line= 4
     1703279.391       173695.28     1703567.306      173530.295
     1703683.765      173332.961     1703890.805      173054.751
#Sta/Elev= 30
    10.1 1229.77    50.3 1205.64   110.6 1165.18   130.7 1152.91   160.9 1136.94
   221.2 1107.16   261.4 1089.53   331.8 1062.53   341.8 1059.69   381.6 1051.81
   391.6 1049.05   411.5 1041.45   416.5  1041.2   421.5 1040.96   426.5 1042.52
   451.4    1050   481.3 1061.93   531.1 1083.44   580.8 1106.02   600.6 1113.62
   620.4 1123.73   640.2 1135.64     670    1156   699.7  1179.3   739.3 1212.69
   759.1 1228.71   788.9 1251.38   808.7 1265.58   818.6 1271.67   907.8 1321.51
#Mann= 3 , 0 , 0
       0     .06       0   416.5    .045       0   426.5     .06       0
Bank Sta=416.5,426.5
XS Rating Curve= 0 ,0
Exp/Cntr=0.3,0.1

Type RM Length L Ch R = 1 ,3727.6  ,248.9,249.1,249.3
XS GIS Cut Line= 4
     1703669.152      173995.174       1703751.7       173649.99
     1703864.925       173391.19     1703957.234       173131.88
#Sta/Elev= 30
     9.9 1187.14    29.6  1175.5      69 1157.98    88.7 1151.72   197.2 1120.71
   216.9 1113.69   256.3 1097.42   266.2 1094.05   285.9 1089.35   305.6  1087.1
   315.5 1085.05   325.3 1081.91   345.1 1073.98   385.2 1054.84   405.4 1046.08
   435.6 1037.54   450.8 1034.91   455.8 1034.49   460.8 1034.89   526.4 1046.49
   536.5 1049.17   546.6 1053.96   556.7 1060.21     587 1080.45   617.2 1099.37
   627.3 1106.74   765.2 1218.55     834 1271.61   843.8    1278   912.7 1315.68
#Mann= 3 , 0 , 0
       0     .06       0   450.8    .045       0   460.8     .06       0
Bank Sta=450.8,460.8
XS Rating Curve= 0 ,0
Exp/Cntr=0.3,0.1

Type RM Length L Ch R = 1 ,3478.6  ,178.7,176.5,174.2
XS GIS Cut Line= 4
      1703842.28      174012.309      1703978.15       173747.04
     1704062.259       173559.41     1704152.839      173242.381
#Sta/Elev= 30
     9.9 1187.76    59.6 1159.05    69.5 1153.77   139.1 1120.69   208.6 1085.14
   258.3 1062.24   268.2 1058.85   288.1 1054.87     298 1052.02   337.2 1035.84
     347 1032.85     391 1026.74     396  1026.3     401 1026.33   415.5 1027.08
   425.3 1028.43   435.1 1030.41   444.9 1033.44   474.3 1044.66   484.1 1049.04
   553.6 1082.31   563.6 1087.64   573.6 1094.28   583.6 1102.21   653.5  1160.4
   703.5 1203.08   783.4 1269.63   793.4 1277.42   803.4 1284.34   833.4 1300.81
#Mann= 3 , 0 , 0
       0     .06       0     391    .045       0     401     .06       0
Bank Sta=391,401
XS Rating Curve= 0 ,0
Exp/Cntr=0.3,0.1

Type RM Length L Ch R = 1 ,3302.1  ,331,330.7,330.3
XS GIS Cut Line= 4
     1704035.127      174180.453     1704133.429      173847.324
     1704211.069      173607.935     1704367.439      173331.317
#Sta/Elev= 30
     9.9 1202.77    39.7 1188.44    89.3  1167.7     129  1152.8   158.8 1142.97
   188.6 1130.87   267.9 1092.63   347.3 1057.17   387.6 1039.74   407.7 1031.63
   427.9 1024.52   437.9  1021.8     443 1021.38     448 1020.97     453 1021.42
   458.1 1021.87   518.5 1034.73   538.6 1039.17   548.7 1041.85   558.7  1045.3
   578.9 1053.57     599 1062.85   628.8 1075.68   638.7 1080.61   648.6 1086.94
   658.6 1094.37   757.9 1173.13   817.5 1218.67   847.2 1241.84   916.8 1294.08
#Mann= 3 , 0 , 0
       0     .06       0     443    .045       0     453     .06       0
Bank Sta=443,453
XS Rating Curve= 0 ,0
Exp/Cntr=0.3,0.1

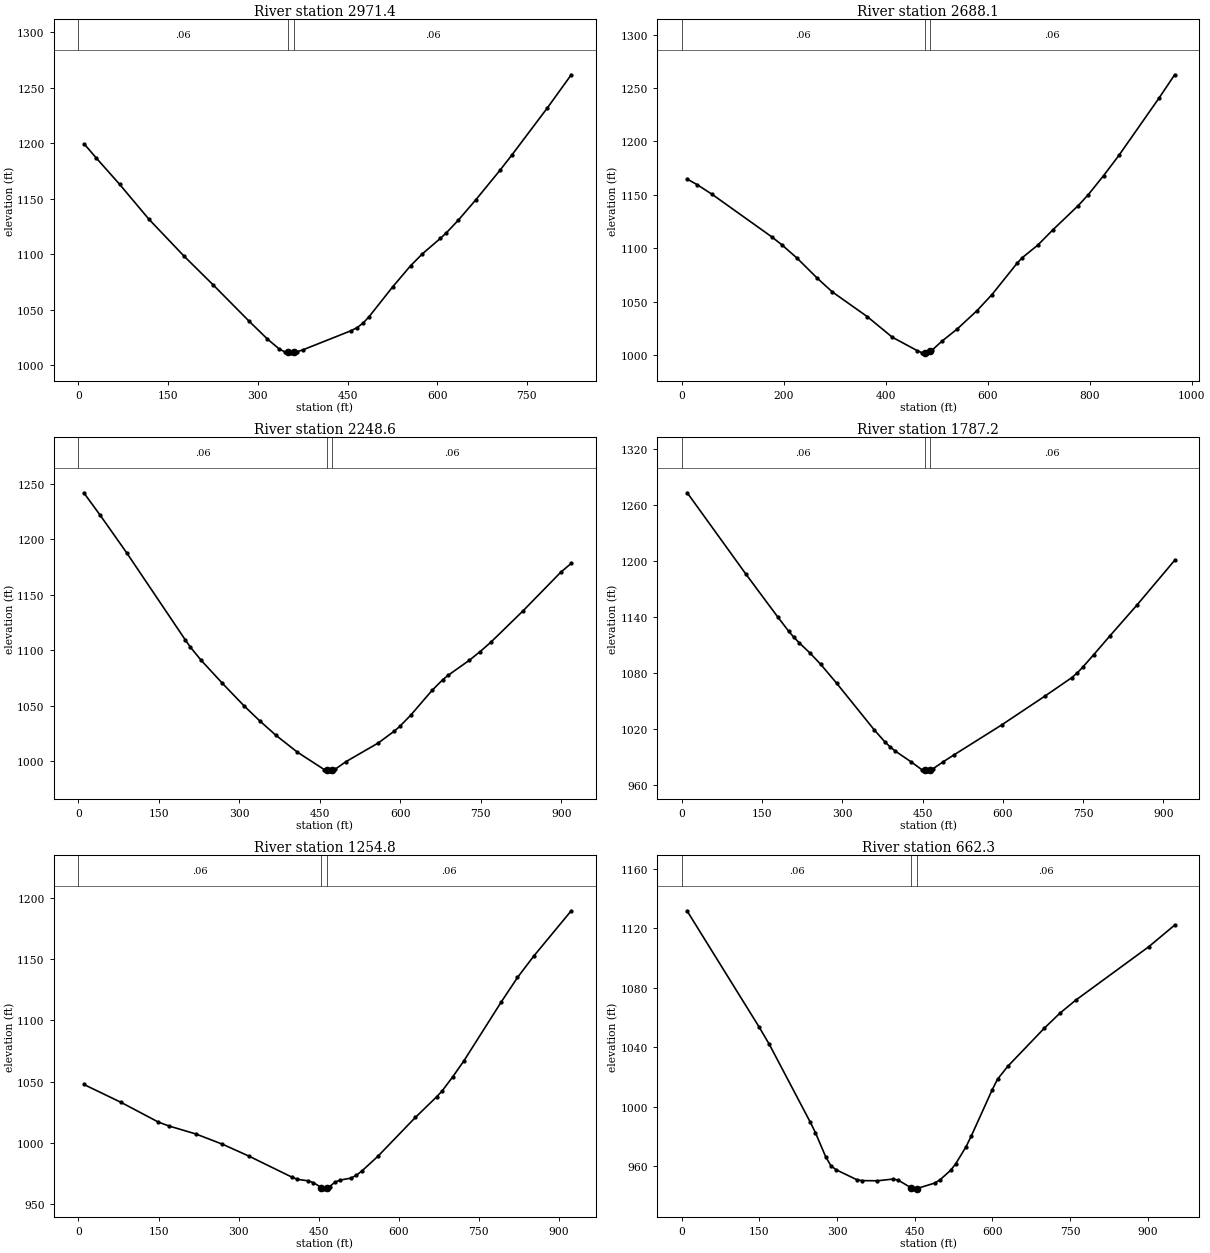
Type RM Length L Ch R = 1 ,2971.4  ,296.7,283.3,269.9
XS GIS Cut Line= 4
     1704369.584      174212.879     1704434.284      173986.429
     1704511.923       173727.63     1704541.038        173410.6
#Sta/Elev= 30
     9.8 1199.16    29.4 1186.86    68.7 1162.99   117.8 1131.47   176.6 1098.19
   225.7 1072.05   285.5 1039.49   315.6  1023.7   335.6 1014.59   345.6 1011.74
   350.6  1011.4   355.6 1011.06   360.6 1011.53   365.6 1012.01   375.6 1013.82
   455.7 1030.97   465.7 1033.71   475.7 1037.77   485.7 1043.43   525.6 1070.62
   555.4 1089.55   575.3 1100.35   605.2  1114.2   615.1 1119.16     635 1130.46
   664.9 1149.24   704.7 1175.46   724.6 1189.19   784.3  1231.9   824.1 1261.66
#Mann= 3 , 0 , 0
       0     .06       0   350.6    .045       0   360.6     .06       0
Bank Sta=350.6,360.6
XS Rating Curve= 0 ,0
Exp/Cntr=0.3,0.1

Type RM Length L Ch R = 1 ,2688.1  ,425.9,439.5,453.1
XS GIS Cut Line= 4
     1704744.843      174361.688     1704799.838      174022.014
     1704702.788      173776.155     1704649.873      173421.909
#Sta/Elev= 30
     9.8 1164.87    29.5 1159.61      59 1150.55     177  1110.4   196.6    1103
   226.1 1090.65   265.4 1072.05   294.9 1059.21   363.7 1035.98   412.6 1016.78
   461.6 1004.18   471.4 1002.15   476.2 1002.13   481.2  1002.1   486.2 1003.42
   490.9 1004.65   510.5 1013.17   539.9 1024.32     579 1041.62   608.4 1056.67
   658.2 1086.35   668.1  1091.3     698 1102.85   727.8 1117.22   777.6 1139.94
   797.5 1150.28   827.3 1167.98   857.2  1186.8   936.7 1241.02   966.6 1262.32
#Mann= 3 , 0 , 0
       0     .06       0   476.2    .045       0   486.2     .06       0
Bank Sta=476.2,486.2
XS Rating Curve= 0 ,0
Exp/Cntr=0.3,0.1

Type RM Length L Ch R = 1 ,2248.6  ,458.2,461.4,464.5
XS GIS Cut Line= 4
     1704945.197      174433.276     1705087.752      174115.829
       1705164.2      173866.138     1705302.817      173589.389
#Sta/Elev= 30
     9.9  1241.9    39.8  1222.1    89.5 1188.04   198.8  1109.5   208.8 1102.62
   228.7 1090.88   268.4 1070.08   308.2 1050.04     338 1036.23   368.1 1023.26
   408.2 1008.03   458.5  992.25   463.5  991.74   468.5  991.23   473.5  991.97
   478.6  992.74   498.6   999.5   558.9 1016.36     589 1027.13   599.1 1031.38
   619.1 1041.26     659 1063.68     679 1073.37     689 1077.32   728.9    1091
   748.9 1098.79   768.9 1107.26   828.8 1135.47   898.7 1170.08   918.6 1178.31
#Mann= 3 , 0 , 0
       0     .06       0   463.5    .045       0   473.5     .06       0
Bank Sta=463.5,473.5
XS Rating Curve= 0 ,0
Exp/Cntr=0.3,0.1

Type RM Length L Ch R = 1 ,1787.2  ,541.6,532.4,523.2
XS GIS Cut Line= 4
     1705332.579      174603.309     1705485.656      174300.223
     1705599.068      174045.862     1705699.555      173760.069
#Sta/Elev= 30
      10 1272.73   119.8 1185.68   179.8 1139.53   199.7 1124.69   209.7 1118.06
   219.7 1112.18   239.7 1101.32   259.7 1089.23   289.6 1068.96   359.4 1019.44
   379.3 1006.57   389.3 1001.14   399.2  996.53   429.1   984.9     449  976.56
   453.9  976.06   458.9  975.54   463.9  976.54   468.9  977.54   488.7  985.32
   508.6   992.6   598.2 1024.78   678.6 1055.44   729.1 1075.27   739.2 1080.32
   749.3 1086.39   769.5 1099.49   799.8 1119.63   850.3 1152.54     921 1200.51
#Mann= 3 , 0 , 0
       0     .06       0   453.9    .045       0   463.9     .06       0
Bank Sta=453.9,463.9
XS Rating Curve= 0 ,0
Exp/Cntr=0.3,0.1

Type RM Length L Ch R = 1 ,1254.8  ,577.3,592.5,607.5
XS GIS Cut Line= 4
     1705970.686      174725.653     1706055.015      174406.978
      1706045.31      174115.829     1706052.682      173813.814
#Sta/Elev= 30
      10 1047.76    79.9 1033.11   149.8 1017.03   169.8 1013.83   219.8 1007.37
   269.7  999.02   319.7  989.22     400  972.11     410  970.37   430.1  969.18
   440.1  967.66   455.2  963.62   460.2  962.61   465.2  963.49   470.3  964.37
   480.3  967.99   490.4   969.8   510.5  971.34   520.5  973.68   530.5  977.01
   560.7  989.07     631 1020.82   671.3 1037.82   681.4 1042.56   701.5 1054.23
   721.7 1066.79   792.1 1115.12   822.4    1135   852.6  1152.3   923.1 1189.42
#Mann= 3 , 0 , 0
       0     .06       0   455.2    .045       0   465.2     .06       0
Bank Sta=455.2,465.2
XS Rating Curve= 0 ,0
Exp/Cntr=0.3,0.1

Type RM Length L Ch R = 1 ,662.3   ,374.7,376.2,377.8
XS GIS Cut Line= 4
      1706220.78      174881.674     1706452.919      174636.663
     1706637.314      174436.093     1706702.418       174099.99
#Sta/Elev= 30
     9.9 1131.84   148.9 1053.88   168.8 1042.13   248.2  989.64   258.1  982.61
     278  966.36   287.9  960.43   297.8  957.73   337.5  951.07   347.6  950.38
   377.9  950.25   408.2  951.42   418.2  950.65   443.5  945.44   448.5  944.84
   453.5  944.97   488.9  948.74     499  950.94   519.2  957.23   529.2  961.67
   549.4  973.31   559.5  980.51   599.9 1011.57     610 1018.56   630.1 1027.34
   700.6 1052.93   730.8 1063.03     761 1071.68     902 1107.58   952.3 1122.18
#Mann= 3 , 0 , 0
       0     .06       0   443.5    .045       0   453.5     .06       0
Bank Sta=443.5,453.5
XS Rating Curve= 0 ,0
Exp/Cntr=0.3,0.1

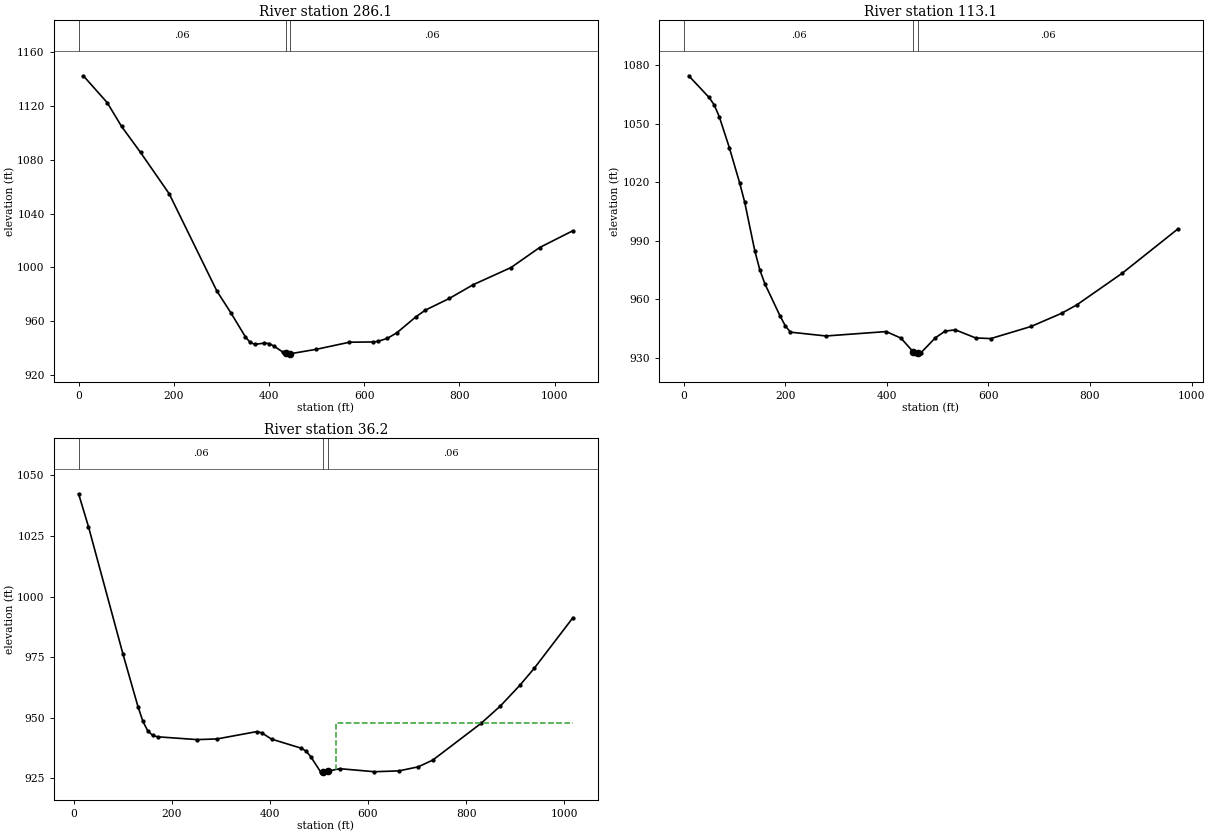
Type RM Length L Ch R = 1 ,286.1   ,182.4,173,163.3
XS GIS Cut Line= 4
      1706460.52      175132.724     1706669.664      174931.047
     1706902.583      174714.303     1707064.333      174316.398
#Sta/Elev= 30
      10 1142.25    60.1 1122.35    90.2 1104.72   130.2 1085.35   190.4 1054.64
   290.5  982.48   320.4  966.04   350.2  948.62   360.1  944.48   370.1   942.9
     390  943.86   399.9  943.51   409.9  941.77   429.7  937.03   434.7  936.47
   439.7   935.9   444.7  935.97   499.3  939.26   568.9  944.52   618.7  944.72
   628.7  945.16   648.7  947.41   668.6  951.56   708.6  963.39   728.6  968.38
   778.5  976.97   828.5  987.15   908.4  999.96   968.3 1014.78  1038.2 1027.25
#Mann= 3 , 0 , 0
       0     .06       0   434.7    .045       0   444.7     .06       0
Bank Sta=434.7,444.7
XS Rating Curve= 0 ,0
Exp/Cntr=0.3,0.1

Type RM Length L Ch R = 1 ,113.1   ,78.8,77,75.3
XS GIS Cut Line= 4
     1706572.614      175173.672     1706886.408      175018.392
     1706941.403      174863.112     1707057.863      174419.918
#Sta/Elev= 30
      10 1074.67      50 1063.55      60 1059.78      70 1053.74      90 1037.73
     110 1019.91     120    1010     140  984.92     150  975.03   160.1  967.86
   190.1  951.32   200.1  946.44   210.1   943.2   280.1  941.24   398.6   943.5
   427.6  940.17   451.7  933.16   456.7  932.08   461.7  932.26   466.4  932.44
   495.5  940.32   514.8  943.73   534.8  944.39   574.6  940.25   604.5   939.9
   684.2  946.14     744  952.88   773.8  957.16   863.5  973.45   973.1  996.17
#Mann= 3 , 0 , 0
       0     .06       0   451.7    .045       0   461.7     .06       0
Bank Sta=451.7,461.7
XS Rating Curve= 0 ,0
Exp/Cntr=0.3,0.1

Type RM Length L Ch R = 1 ,36.2    ,32.3,36.2,40.1
XS GIS Cut Line= 4
     1706625.288      175231.733     1706971.473      175024.755
     1707046.571        174755.5     1707075.877      174422.138
#Sta/Elev= 30
    10.1 1042.37    30.3  1028.8   100.8  976.12   131.1  954.66   141.2  948.54
   151.3  944.54   161.3  942.73   171.4  942.16   252.1  941.01   292.4  941.29
   373.1   944.3   383.2  943.83   403.3  941.22   463.2  937.51   473.2  936.37
   483.2  934.01   503.2  927.74   508.2  927.73   513.2  927.72   518.2  928.04
   543.1  929.01     613  927.77   662.9  928.11   702.6   929.8   732.1  932.58
   830.5  947.73   869.9   954.9   909.3  963.38   938.8  970.42  1017.5  991.25
#Mann= 3 , 0 , 0
    10.1     .06       0   508.2    .045       0   518.2     .06       0
#XS Ineff= 2 , 0
                          534.47          947.87
Permanent Ineff=
       F       F
Bank Sta=508.2,518.2
XS Rating Curve= 0 ,0
Exp/Cntr=0.3,0.1
Stream Node=Greenbrier Fork ,Main            , 0 , 0 ,Upstream end
Stream Node=Greenbrier Fork ,Main            , 0 , 1 ,Downstream end

Chan Stop Cuts=-1
Use User Specified Reach Order=0